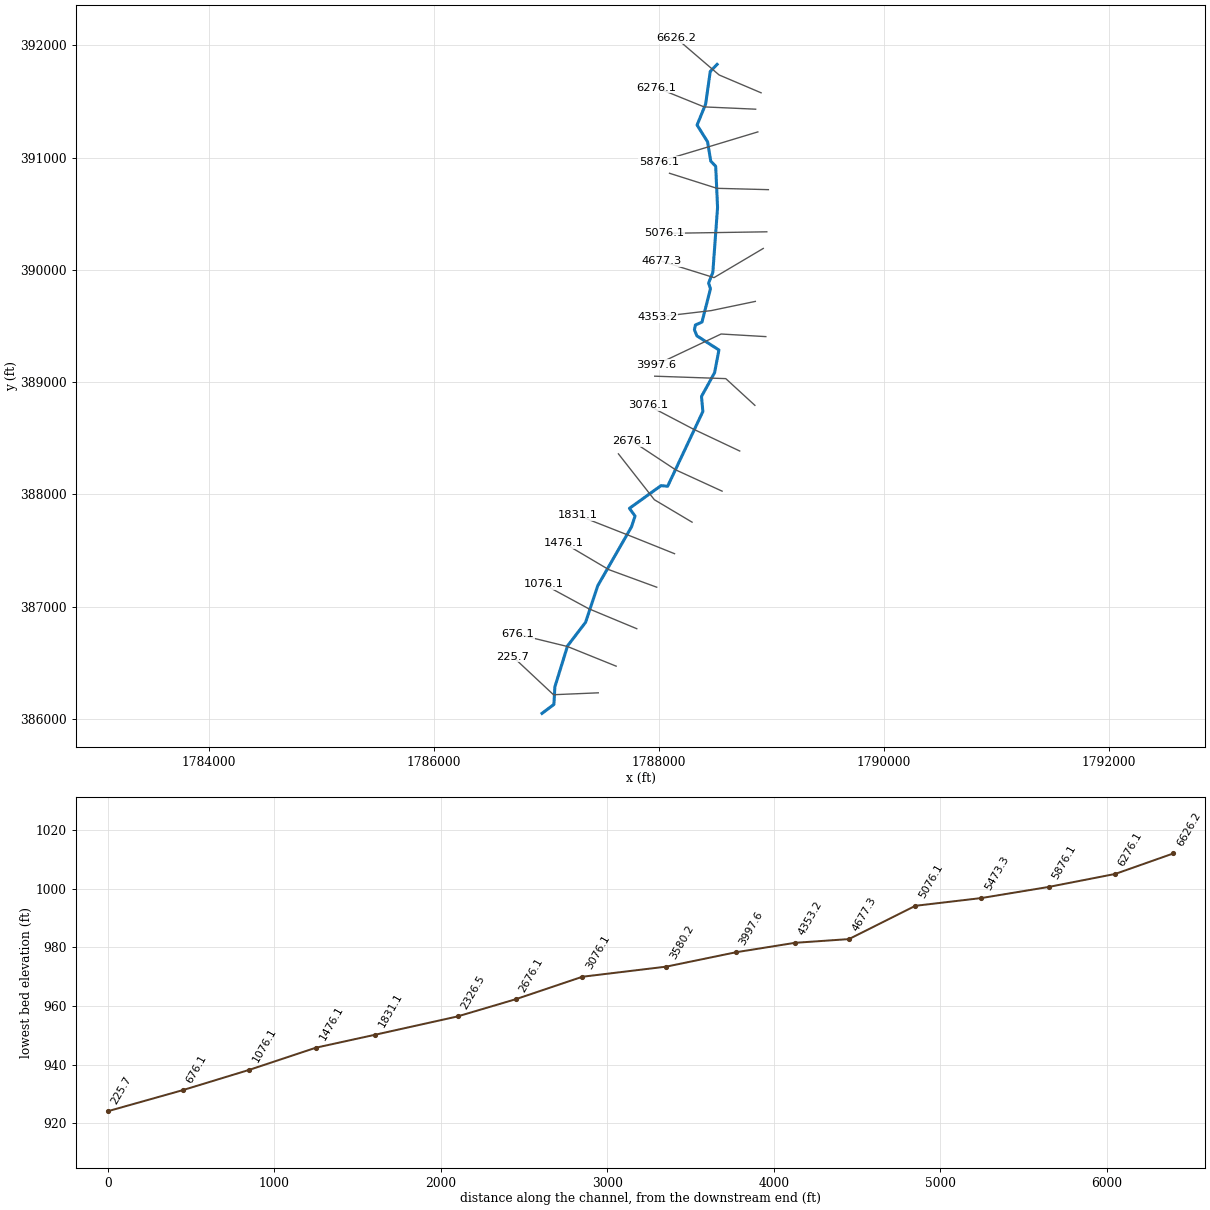
--- MnstrsRn.prj (project) ---

Proj Title=MnstrsRn
Current Plan=p01
Default Exp/Contr=0,0
English Units
Geom File=g01
Flow File=f01
Plan File=p01
BEGIN DESCRIPTION:
END DESCRIPTION:
DSS Export Rating Curves= 0
DSS Export Rating Curve Sorted= 0
DSS Export Volume Flow Curves= 0
DXF OffsetX= 0
DXF OffsetY= 0
DXF ScaleX= 0
DXF ScaleY= 0

--- MnstrsRn.p01 (plan) ---

Plan Title=Floodplain
Program Version=4.00
Geom File=g01
Flow File=f01
K Sum by GR=0
Std Step Tol=0.01
Critical Tol=0.01
Num of Std Step Trials=20
Max Error Tol=0.3
Flow Tol Ratio=0.001
Split Flow NTrial=30
Split Flow Tol=0.02
Split Flow Ratio=0.02
Log Output Level=0
Friction Slope Method=1
Unsteady Friction Slope Method=2
Unsteady Bridges Friction Slope Method=1
Global Log Level=0
CheckData=False
Run HTab=0
Run UNet=0
Run PostProcess=0
UNET Theta=0
UNET Theta Warmup=0
UNET ZTol=0
UNET ZSATol=0
UNET MxIter=0
UNET MaxInSteps=0
UNET DtIC=0
UNET DtMin=0
UNET MaxCRTS=0
UNET WFStab=0
UNET SFStab=0
UNET WFX=0
UNET SFX=0
UNET DSS MLevel=0
UNET DZMax Abort=0
UNET Convert EG Bridges=0
UNET Use Existing IB Tables=0
UNET Froude Limit=0
UNET Froude Power=0
Write IC File=0
Echo Input=False
Echo Output=False
Write Detailed=0

--- MnstrsRn.f01 (steady flow) ---

Flow Title=NFF Regression Equation
Program Version=4.00
Number of Profiles=1
Profile Names=P100yr
River Rch & RM=MnstrsRn,Main      ,6626.2
824.3312
River Rch & RM=MnstrsRn,Main      ,5473.3
839.8998
River Rch & RM=MnstrsRn,Main      ,3997.6
929.4883
River Rch & RM=MnstrsRn,Main      ,225.7
1023.691
Boundary for River Rch & Prof#=MnstrsRn,Main      ,1
Up Type=0
Dn Type=3
Dn Slope=0.015323

--- MnstrsRn.g01 (geometry) ---

Geom Title=USGS 3m DEM
Program Version=4.00

River Reach=MnstrsRn     ,Main
Reach XY= 30
     1788519.782      391830.188     1788459.018      391767.254
     1788417.785      391476.456     1788341.830      391289.824
     1788435.146      391140.084     1788463.358      390968.643
     1788507.270      390922.300     1788523.866      390556.082
     1788481.823      389977.436     1788444.205      389882.286
     1788460.802      389831.392     1788385.566      389534.877
     1788326.927      389508.324     1788318.076      389466.280
     1788340.204      389412.067     1788536.036      389285.938
     1788497.313      389083.467     1788381.141      388872.145
     1788393.311      388738.271     1788080.201      388072.220
     1788021.562      388077.752     1787740.537      387875.281
     1787790.325      387806.684     1787759.345      387711.534
     1787458.405      387184.889     1787351.085      386860.714
     1787190.657      386650.499     1787077.804      386285.387
     1787068.953      386128.279     1786963.308      386048.903

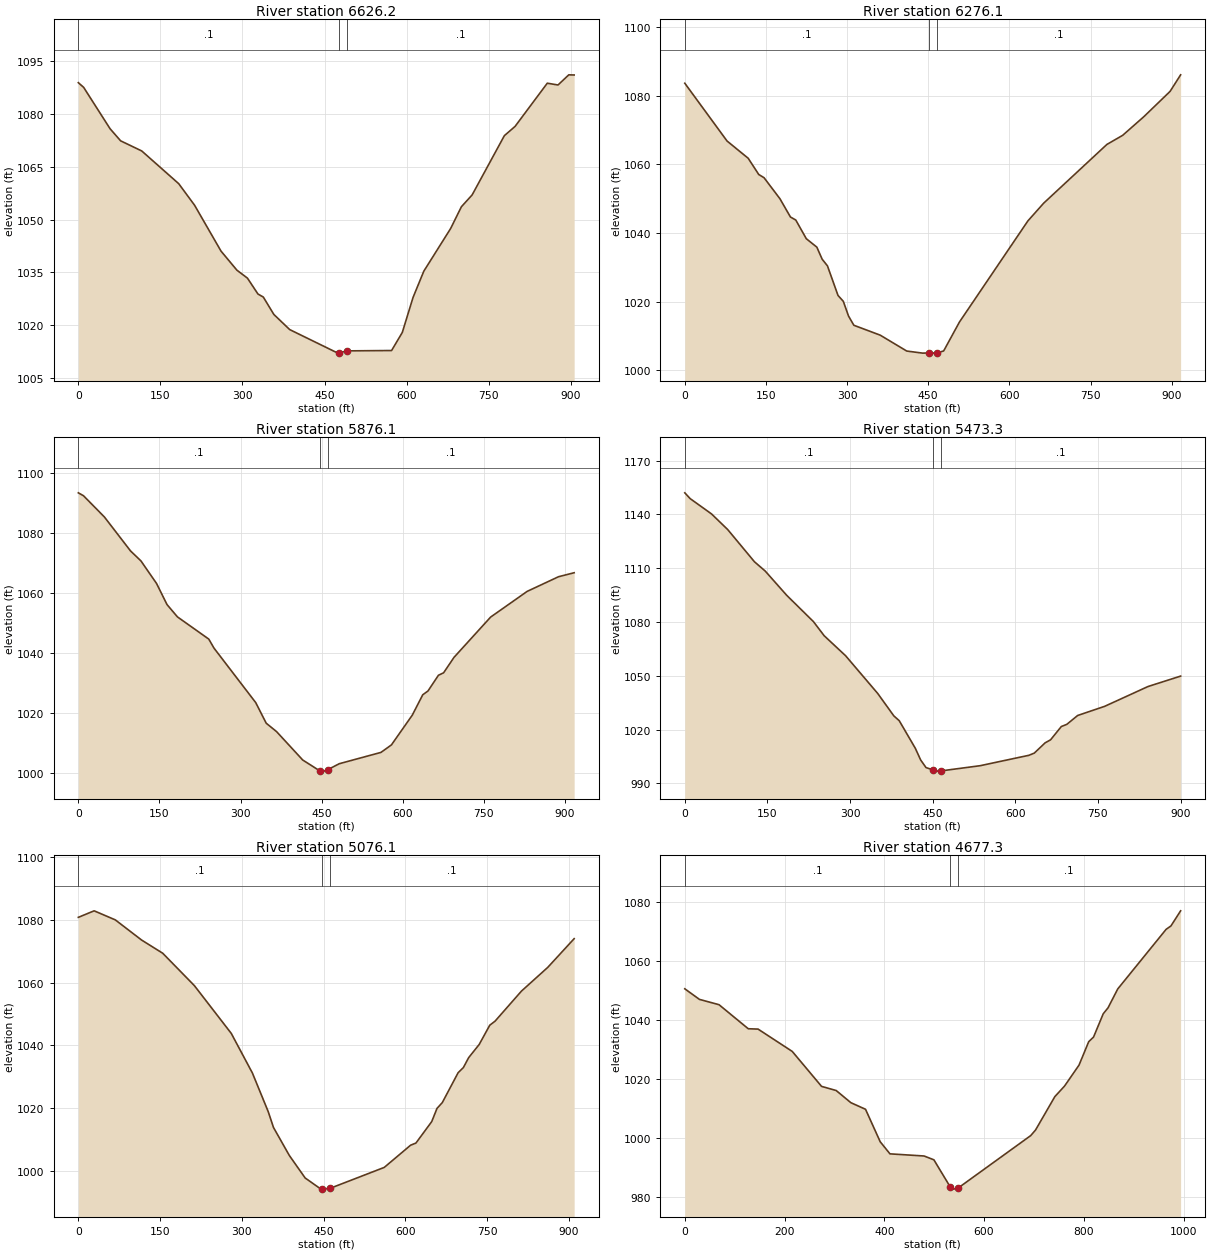
Type RM Length L Ch R = 1 ,6626.2,333.728,350.07,357.941
XS GIS Cut Line= 3
     1788910.926      391577.030     1788537.645      391735.950
     1788157.991      392062.215
#Sta/Elev= 30
       0 1088.95     9.7 1087.62    58.0 1075.85    77.3 1072.41   115.9 1069.53
   183.5 1060.22   212.5 1054.09   260.8 1041.05   289.8 1035.63   309.1 1033.36
   328.4 1028.83   338.1 1027.98   357.4 1023.03   386.4 1018.72   474.4 1012.03
   476.6 1012.11   491.6 1012.67   572.6 1012.77   592.2 1017.92   611.8 1027.86
   631.5 1035.34   680.5 1047.46   700.2 1053.66   719.8 1057.02   778.7 1073.87
   798.3 1076.51   857.2 1088.80   876.8 1088.29   896.5 1091.18   906.3 1091.13
#Mann= 3 , 0 , 0
       0     0.1       0   476.6   0.045       0   491.6     0.1       0
Bank Sta=   476.6,   491.6
Exp/Cntr=0.3,0.1

Type RM Length L Ch R = 1 ,6276.1,388.857,400,417.505
XS GIS Cut Line= 3
     1788862.511      391431.050     1788403.972      391451.460
     1787980.123      391623.691
#Sta/Elev= 30
       0 1083.68    78.1 1066.84   117.2 1061.81   136.7 1057.08   146.5 1056.14
   175.8 1050.03   195.3 1044.69   205.1 1043.82   224.6 1038.37   244.1 1035.90
   253.9 1032.40   263.7 1030.45   283.2 1021.83   293.0 1020.12   302.7 1015.81
   312.5 1013.14   361.3 1010.25   410.2 1005.63   439.5 1005.02   451.5 1005.06
   466.5 1005.09   478.5 1005.66   507.7 1014.09   634.2 1043.56   663.4 1048.73
   780.2 1065.84   809.4 1068.50   848.4 1073.91   897.0 1081.30   916.5 1086.13
#Mann= 3 , 0 , 0
       0     0.1       0   451.5   0.045       0   466.5     0.1       0
Bank Sta=   451.5,   466.5
Exp/Cntr=0.3,0.1

Type RM Length L Ch R = 1 ,5876.1,408.225,402.801,390.442
XS GIS Cut Line= 3
     1788882.185      391228.721     1788448.144      391097.193
     1788004.414      390963.898
#Sta/Elev= 30
       0 1093.41     9.6 1092.43    48.2 1085.36    96.5 1074.04   115.8 1070.70
   144.7 1063.16   164.0 1056.14   183.3 1052.03   241.2 1044.63   250.9 1041.61
   328.1 1023.43   347.4 1016.58   366.7 1013.75   414.9 1004.31     446 1000.74
   453.5 1000.59     461 1001.05   482.5 1003.06   559.7 1006.84   579.0 1009.34
   617.6 1019.27   636.9 1026.05   646.6 1027.32   665.9 1032.56   675.5 1033.39
   694.8 1038.55   762.4 1051.96   830.0 1060.54   887.9 1065.42   916.9 1066.76
#Mann= 3 , 0 , 0
       0     0.1       0     446   0.045       0     461     0.1       0
Bank Sta=     446,     461
Exp/Cntr=0.3,0.1

Type RM Length L Ch R = 1 ,5473.3,396.291,397.199,404.59
XS GIS Cut Line= 3
     1788975.875      390714.231     1788518.628      390726.173
     1788096.779      390860.283
#Sta/Elev= 30
       0 1152.00     9.7 1148.78    48.7 1140.19    77.9 1131.51   126.5 1113.54
   146.0 1108.37   184.9 1094.89   233.6 1080.16   253.0 1072.32   292.0 1061.13
   350.4 1040.05   379.5 1027.61   389.3 1024.92   418.5 1009.54   428.2 1003.02
   437.9  998.79     450  997.57   457.4  996.81     465  996.93   536.1  999.83
   624.6 1005.63   634.5 1006.87   654.1 1012.58   664.0 1014.27   683.6 1021.70
   693.5 1022.89   713.2 1027.84   762.3 1032.95   841.0 1044.00   900.1 1049.80
#Mann= 3 , 0 , 0
       0     0.1       0     450   0.045       0     465     0.1       0
Bank Sta=     450,     465
Exp/Cntr=0.3,0.1

Type RM Length L Ch R = 1 ,5076.1,406.053,398.783,391.513
XS GIS Cut Line= 3
     1788961.821      390338.734     1788506.875      390331.736
     1788051.928      390324.738
#Sta/Elev= 30
       0 1080.85    29.0 1082.93    67.8 1080.05   116.2 1073.60   154.9 1069.40
   213.0 1059.07   280.7 1043.83   319.5 1031.19   348.5 1018.88   358.2 1013.82
   387.2 1004.91   416.3  997.72   445.3  994.16   447.5  994.16   462.5  994.44
   561.5 1001.09   609.9 1008.18   619.6 1008.85   648.6 1015.70   658.3 1019.92
   668.0 1021.76   697.0 1031.28   706.7 1032.94   716.4 1036.10   735.7 1040.30
   755.1 1046.44   764.8 1047.73   813.2 1057.31   861.6 1064.90   910.0 1074.05
#Mann= 3 , 0 , 0
       0     0.1       0   447.5   0.045       0   462.5     0.1       0
Bank Sta=   447.5,   462.5
Exp/Cntr=0.3,0.1

Type RM Length L Ch R = 1 ,4677.3,313.916,324.134,334.352
XS GIS Cut Line= 3
     1788930.324      390190.621     1788492.360      389930.668
     1788029.642      390075.592
#Sta/Elev= 30
       0 1050.55    29.4 1046.97    68.6 1045.18   127.3 1037.04   146.9 1036.93
   215.5 1029.37   274.2 1017.56   303.6 1016.15   333.0 1012.04   362.4 1009.81
   391.8  998.84   411.4  994.74   479.9  994.01   499.5  992.72   532.5  983.48
   538.4  982.81   547.5  983.11   693.6 1000.91   703.3 1002.80   742.0 1014.09
   761.4 1017.65   790.5 1024.75   809.9 1032.67   819.6 1034.23   839.0 1042.10
   848.7 1044.13   868.1 1050.50   965.1 1070.66   974.8 1071.81   994.2 1076.92
#Mann= 3 , 0 , 0
       0     0.1       0   532.5   0.045       0   547.5     0.1       0
Bank Sta=   532.5,   547.5
Exp/Cntr=0.3,0.1

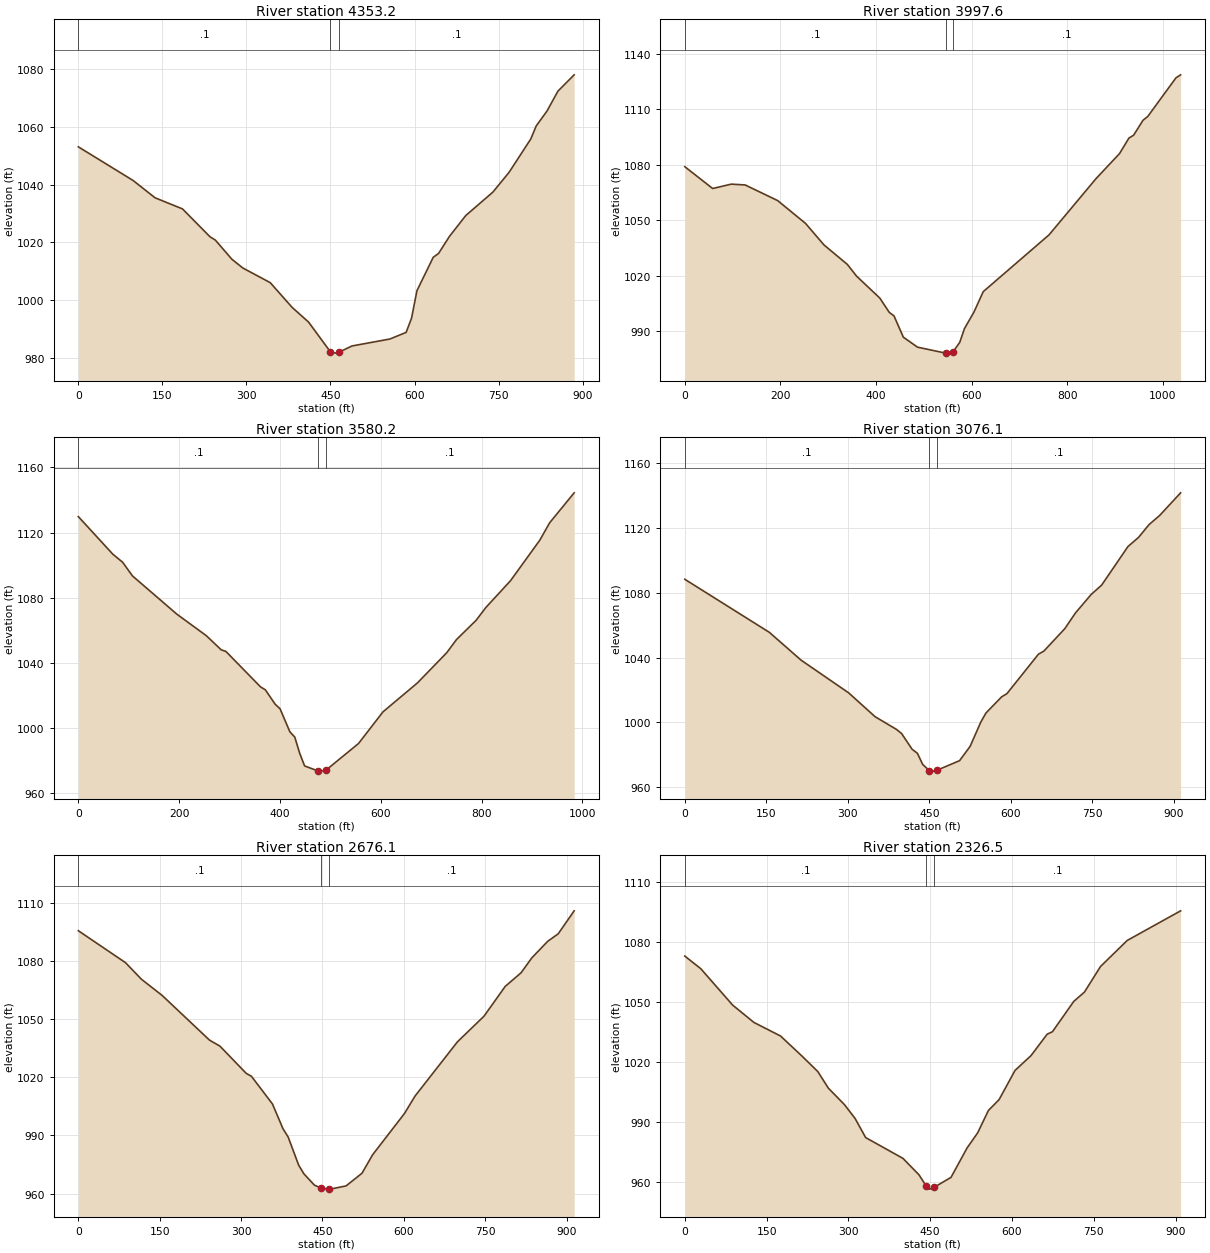
Type RM Length L Ch R = 1 ,4353.2,351.633,355.591,360.674
XS GIS Cut Line= 3
     1788859.685      389718.750     1788466.930      389636.808
     1787986.581      389580.297
#Sta/Elev= 30
       0 1053.08    97.9 1041.39   137.0 1035.40   185.9 1031.56   234.9 1021.91
   244.6 1020.73   274.0 1014.11   293.6 1011.06   342.5 1005.98   381.6  997.40
   410.9  992.31   449.6  982.06   459.3  981.54   464.6  981.80   488.3  984.02
   556.0  986.43   585.0  988.73   594.7  993.66   604.3 1003.19   633.4 1014.77
   643.0 1016.13   662.4 1022.04   691.4 1029.24   739.8 1037.37   768.8 1044.25
   807.5 1055.81   817.2 1060.33   836.5 1065.51   855.9 1072.38   884.9 1078.05
#Mann= 3 , 0 , 0
       0     0.1       0   449.6   0.045       0   464.6     0.1       0
Bank Sta=   449.6,   464.6
Exp/Cntr=0.3,0.1

Type RM Length L Ch R = 1 ,3997.6,420.296,417.406,413.496
XS GIS Cut Line= 3
     1788952.929      389405.111     1788555.442      389428.362
     1787978.365      389154.371
#Sta/Elev= 30
       0 1079.05    58.3 1067.26    97.1 1069.62   126.2 1069.19   194.2 1060.74
   252.5 1048.41   291.3 1036.73   339.9 1026.27   359.3 1019.90   408.0 1008.02
   427.7 1000.31   437.5  998.45   457.1  986.93   486.6  981.54   545.6  978.31
   546.6  978.31   561.6  979.16   575.1  984.17   584.9  991.57   604.6 1000.41
   624.2 1011.54   761.8 1042.22   860.1 1072.61   909.2 1086.12   928.9 1094.53
   938.7 1096.07   958.4 1104.16   968.2 1106.16  1027.2 1127.05  1037.0 1128.69
#Mann= 3 , 0 , 0
       0     0.1       0   546.6   0.045       0   561.6     0.1       0
Bank Sta=   546.6,   561.6
Exp/Cntr=0.3,0.1

Type RM Length L Ch R = 1 ,3580.2,517.817,504.086,488.345
XS GIS Cut Line= 3
     1788855.701      388792.794     1788596.966      389030.911
     1787965.399      389052.642
#Sta/Elev= 30
       0 1129.77    68.4 1106.69    87.9 1101.73   107.4 1093.34   195.3 1069.88
   254.0 1056.60   283.3 1047.97   293.0 1046.88   361.4 1025.19   371.1 1023.34
   390.5 1014.51   400.2 1011.71   419.7  997.57   429.4  994.31   439.1  984.44
   448.9  976.60     476  973.47   478.0  973.42     491  973.95   555.8  990.37
   604.4 1009.84   672.5 1027.55   730.8 1046.14   750.2 1054.24   789.1 1066.06
   808.6 1073.99   857.2 1090.32   915.5 1115.30   935.0 1125.97   983.6 1144.37
#Mann= 3 , 0 , 0
       0     0.1       0     476   0.045       0     491     0.1       0
Bank Sta=     476,     491
Exp/Cntr=0.3,0.1

Type RM Length L Ch R = 1 ,3076.1,399.743,400,397.679
XS GIS Cut Line= 3
     1788720.957      388385.966     1788307.570      388581.664
     1787904.416      388793.363
#Sta/Elev= 30
       0 1088.22   155.7 1055.50   214.1 1038.36   301.7 1018.20   350.3 1003.51
   389.3  995.76   399.0  993.18   418.4  983.46   428.2  980.96   437.9  974.10
   449.9  970.34   457.4  969.97   464.9  970.61   505.8  976.42   525.2  985.22
   544.6 1000.00   554.3 1005.78   583.3 1015.77   593.0 1017.74   651.1 1042.10
   660.8 1043.90   699.6 1057.82   719.0 1067.41   748.0 1078.85   767.4 1084.65
   815.8 1108.41   835.2 1114.01   854.6 1121.92   874.0 1127.51   912.7 1141.50
#Mann= 3 , 0 , 0
       0     0.1       0   449.9   0.045       0   464.9     0.1       0
Bank Sta=   449.9,   464.9
Exp/Cntr=0.3,0.1

Type RM Length L Ch R = 1 ,2676.1,361.718,349.625,339.98
XS GIS Cut Line= 3
     1788564.312      388028.477     1788151.344      388218.325
     1787768.231      388471.985
#Sta/Elev= 30
       0 1095.69    87.0 1079.20   116.0 1070.73   154.7 1062.24   241.8 1039.22
   261.1 1036.11   309.5 1022.06   319.1 1020.56   357.8 1006.29   377.2  993.53
   386.8  989.21   406.2  974.67   415.8  970.22   435.2  964.36     447  962.92
     462  962.32   464.3  962.31   493.6  963.98   522.9  970.51   542.5  980.05
   601.2 1001.35   620.7 1010.35   698.9 1038.36   747.8 1051.57   786.9 1066.95
   816.2 1073.99   835.8 1081.62   865.1 1090.18   884.7 1094.12   914.0 1105.96
#Mann= 3 , 0 , 0
       0     0.1       0     447   0.045       0     462     0.1       0
Bank Sta=     447,     462
Exp/Cntr=0.3,0.1

Type RM Length L Ch R = 1 ,2326.5,473.581,495.38,509.765
XS GIS Cut Line= 3
     1788297.395      387752.147     1787962.248      387952.081
     1787642.585      388360.835
#Sta/Elev= 30
       0 1072.90    29.3 1066.60    87.8 1048.39   126.8 1039.73   175.6 1032.95
   214.6 1023.00   243.9 1015.19   263.4 1006.85   292.7  998.69   312.2  991.79
   331.7  982.19   400.0  971.82   429.4  963.61   442.8  957.95   449.0  956.44
   457.8  957.43   488.2  962.33   517.5  976.96   537.1  984.60   556.7  995.73
   576.3 1001.16   605.6 1015.77   635.0 1023.20   664.4 1033.84   674.2 1035.11
   713.3 1050.26   732.9 1054.92   762.3 1067.69   811.3 1080.71   909.2 1095.51
#Mann= 3 , 0 , 0
       0     0.1       0   442.8   0.045       0   457.8     0.1       0
Bank Sta=   442.8,   457.8
Exp/Cntr=0.3,0.1

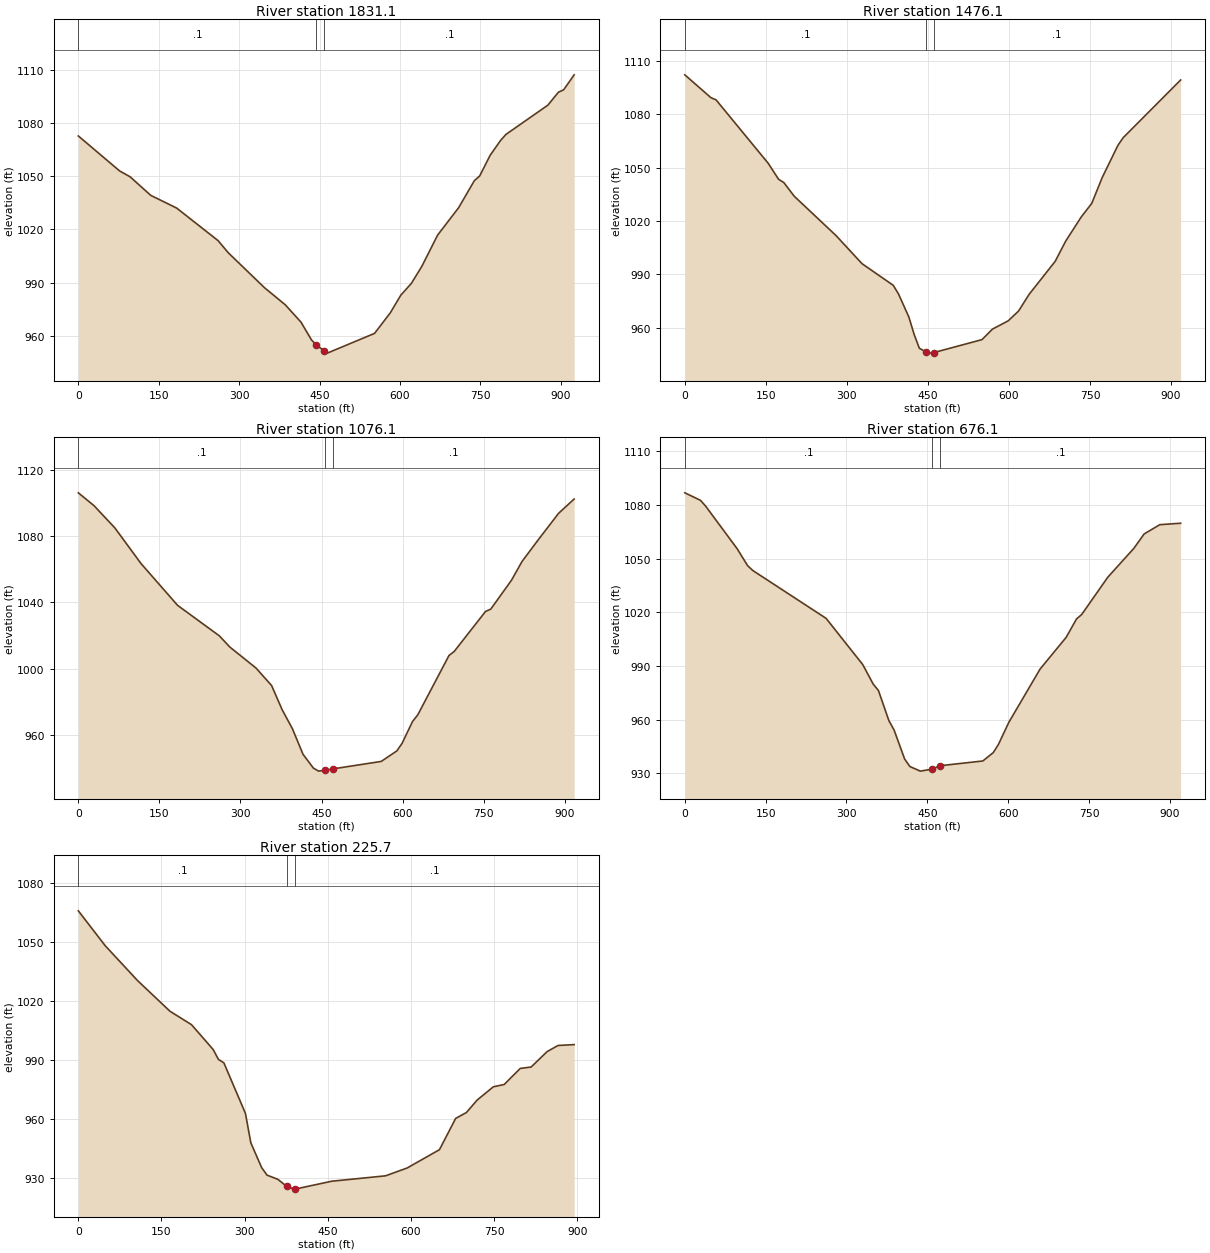
Type RM Length L Ch R = 1 ,1831.1,354.413,354.996,351.424
XS GIS Cut Line= 3
     1788141.411      387471.425     1787783.284      387615.521
     1787281.946      387813.189
#Sta/Elev= 30
       0 1072.69    77.2 1052.92    96.5 1049.68   135.1 1039.18   183.4 1032.02
   260.6 1013.67   279.9 1006.74   347.4  987.06   386.0  977.46   415.4  967.65
   435.0  957.61     444  954.78     459  951.33   464.4  950.19   552.6  961.33
   582.0  972.96   601.6  982.90   621.2  989.52   640.8  999.15   670.2 1016.76
   709.4 1032.22   738.8 1047.51   748.6 1050.08   768.2 1061.80   787.8 1070.21
   797.6 1073.54   875.9 1090.07   895.5 1097.36   905.3 1098.72   924.9 1107.17
#Mann= 3 , 0 , 0
       0     0.1       0     444   0.045       0     459     0.1       0
Bank Sta=     444,     459
Exp/Cntr=0.3,0.1

Type RM Length L Ch R = 1 ,1476.1,401.304,400,400.543
XS GIS Cut Line= 3
     1787983.192      387172.770     1787557.644      387329.095
     1787158.100      387565.685
#Sta/Elev= 30
       0 1102.07    48.2 1089.28    57.9 1087.99   154.3 1052.42   173.6 1043.40
   183.3 1041.57   202.6 1033.87   279.7 1011.87   328.0  996.02   385.8  983.87
   395.5  979.04   414.8  966.00   424.4  956.37   434.1  948.52   445.9  946.55
   453.4  945.78   460.9  946.09   550.1  953.37   569.4  959.25   598.5  963.90
   617.8  969.42   637.2  978.76   685.5  997.31   704.9 1008.64   733.9 1022.31
   753.2 1029.86   772.6 1044.41   801.6 1062.44   811.3 1066.74   917.7 1099.17
#Mann= 3 , 0 , 0
       0     0.1       0   445.9   0.045       0   460.9     0.1       0
Bank Sta=   445.9,   460.9
Exp/Cntr=0.3,0.1

Type RM Length L Ch R = 1 ,1076.1,400.175,400,405.628
XS GIS Cut Line= 3
     1787805.837      386803.033     1787377.692      386981.585
     1786979.191      387197.913
#Sta/Elev= 30
       0 1106.08    29.0 1098.35    67.6 1084.92   116.0 1063.42   183.6 1038.23
   260.9 1019.82   280.3 1013.07   328.6 1000.44   357.6  989.83   376.9  975.39
   396.2  963.73   415.6  948.44   434.9  940.04   444.6  938.23   456.4  938.81
   471.4  939.60   560.4  944.09   589.3  950.43   599.0  955.00   618.2  968.12
   627.9  972.12   685.8 1008.00   695.4 1010.41   753.3 1034.53   763.0 1035.93
   801.5 1053.43   820.8 1064.65   849.8 1077.29   888.4 1093.69   917.3 1102.35
#Mann= 3 , 0 , 0
       0     0.1       0   456.4   0.045       0   471.4     0.1       0
Bank Sta=   456.4,   471.4
Exp/Cntr=0.3,0.1

Type RM Length L Ch R = 1 ,676.1,440.487,450.387,449.428
XS GIS Cut Line= 3
     1787622.451      386469.456     1787190.383      386644.337
     1786749.537      386752.435
#Sta/Elev= 30
       0 1086.81    29.1 1082.63    38.8 1079.33    97.1 1055.60   116.5 1046.14
   126.2 1043.40   262.2 1016.66   330.2  990.83   349.6  979.93   359.3  976.35
   378.7  959.51   388.4  954.24   407.9  938.07   417.6  933.88   437.0  931.30
   458.6  932.38   473.6  934.32   553.0  936.97   572.4  941.66   582.0  946.25
   601.3  958.60   659.3  988.36   707.6 1006.05   726.9 1016.36   736.5 1018.84
   784.8 1039.63   833.1 1055.73   852.4 1063.85   881.4 1069.02   920.0 1069.82
#Mann= 3 , 0 , 0
       0     0.1       0   458.6   0.045       0   473.6     0.1       0
Bank Sta=   458.6,   473.6
Exp/Cntr=0.3,0.1

Type RM Length L Ch R = 1 ,225.7,252.059,225.733,206.771
XS GIS Cut Line= 3
     1787463.849      386231.986     1787065.443      386215.033
     1786703.769      386554.102
#Sta/Elev= 30
       0 1065.87    48.6 1048.07   107.0 1030.30   165.3 1014.73   204.2 1007.87
   243.2  995.25   252.9  990.14   262.6  988.42   301.5  962.67   311.2  947.71
   330.7  935.08   340.4  931.24   359.9  929.12     376  925.49   389.0  924.11
     391  924.12   457.1  928.13   554.3  930.89   593.2  934.87   651.5  944.20
   680.7  960.12   700.1  963.13   719.6  969.51   748.7  976.23   768.2  977.40
   797.3  985.59   816.8  986.30   845.9  994.20   865.4  997.28   894.5  997.72
#Mann= 3 , 0 , 0
       0     0.1       0     376   0.045       0     391     0.1       0
Bank Sta=     376,     391
Exp/Cntr=0.3,0.1